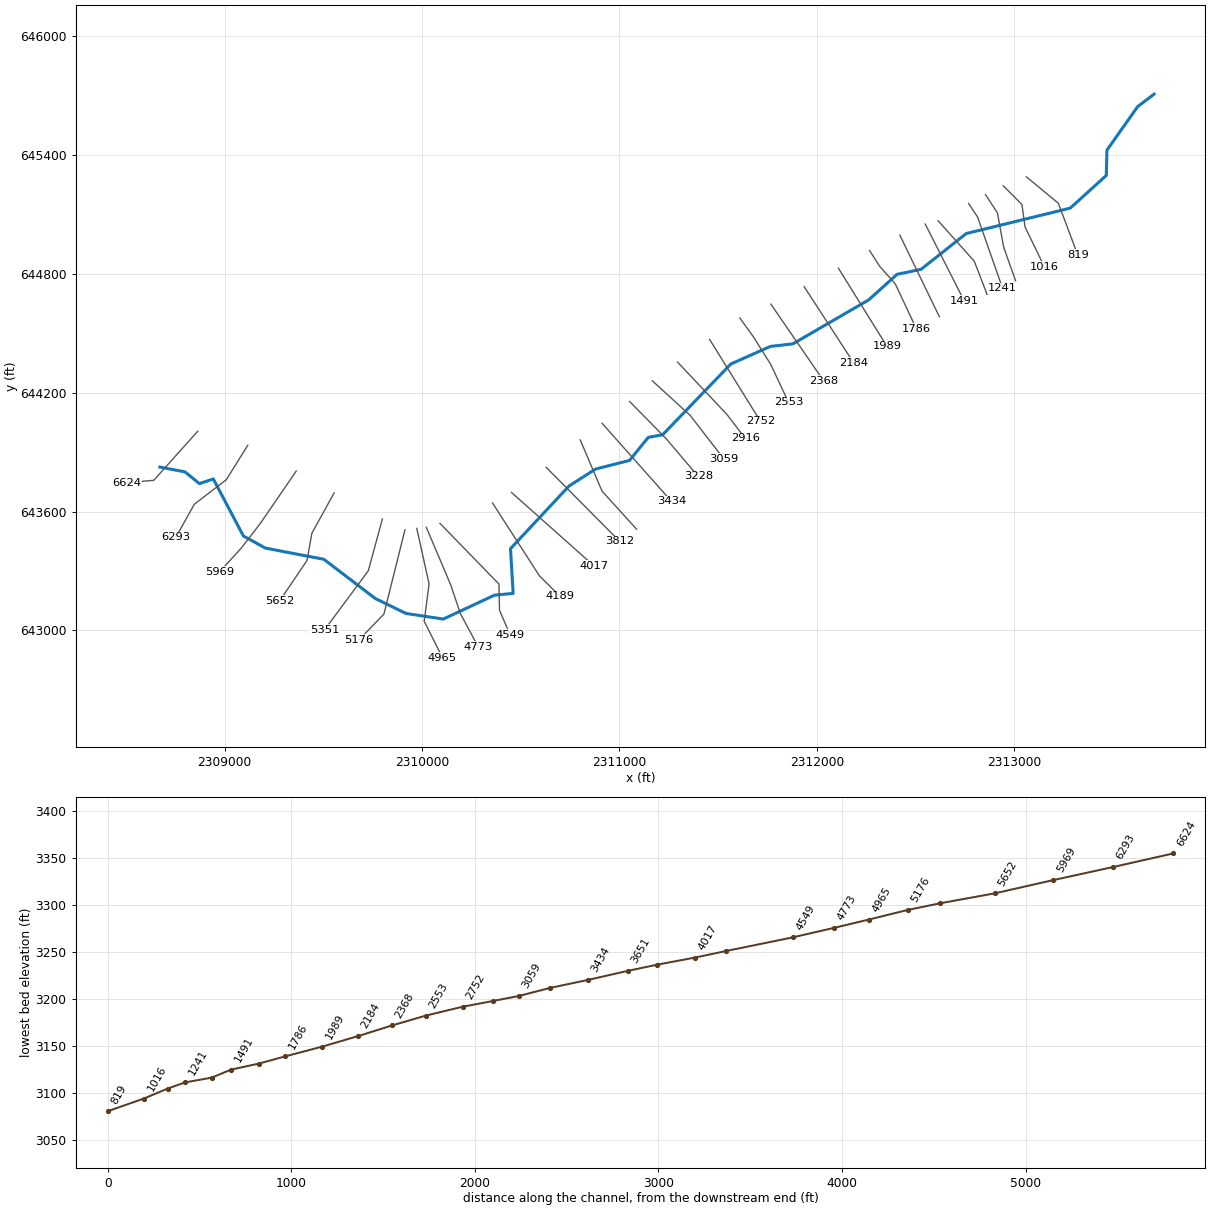
--- ROSERN.prj (project) ---

Proj Title=ROSERN
Current Plan=p01
Default Exp/Contr=0,0
English Units
Geom File=g01
Flow File=f01
Plan File=p01
BEGIN DESCRIPTION:
----------MODEL BY WOOD PLC 2022----------
AFH study
Randolph County, WV
HEC-RAS Version: RAS 6.2
Vertical Datum: NAVD88
Projection: NAD 1983 StatePlane West Virginia S FIPS 4702 (US Feet)
Terrain: 1-meter LIDAR (FEMA Region III 3DEP collected 2016-2018)
Land Use: 2019 NLCD
Hydrologic Method:
WV SIR2010-5033 regression equations
Additional Model Notes:
KWSE tie-in at downstream boundary with REDRN
END DESCRIPTION:
DSS Export Rating Curves= 0
DSS Export Rating Curve Sorted= 0
DSS Export Volume Flow Curves= 0
DXF OffsetX= 0
DXF OffsetY= 0
DXF ScaleX= 0
DXF ScaleY= 0

--- ROSERN.p01 (plan) ---

Plan Title=Floodplain
Program Version=6.20
Short Identifier=Floodplain
Geom File=g01
Flow File=f01
Subcritical Flow
K Sum by GR= 0
Std Step Tol= 0.01
Critical Tol= 0.01
Num of Std Step Trials= 20
Max Error Tol= 0.3
Flow Tol Ratio= 0.001
Split Flow NTrial= 30
Split Flow Tol= 0.02
Split Flow Ratio= 0.02
Log Output Level= 0
Friction Slope Method= 1
Unsteady Friction Slope Method= 2
Unsteady Bridges Friction Slope Method= 1
Parabolic Critical Depth
Global Vel Dist= 0 , 0 , 0
Global Log Level= 0
CheckData=True
Encroach Param=-1 ,0,0, 0
Mapping Interval=1HOUR
Computation Time Step Use Courant=        0
Computation Time Step Use Time Series=    0
Computation Time Step Count To Double=0
Computation Time Step Max Doubling=0
Computation Time Step Max Halving=0
Computation Time Step Residence Courant=0
Run HTab= 0
Run UNet= 0
Run Sediment= 0
Run PostProcess= 0
Run WQNet= 0
Run RASMapper=-1
UNET Theta= 0
UNET Theta Warmup= 0
UNET ZTol= 0
UNET ZSATol= 0
UNET MxIter= 0
UNET Max Iter WO Improvement= 0
UNET MaxInSteps= 0
UNET DtIC= 0
UNET DtMin= 0
UNET MaxCRTS= 0
UNET WFStab= 0
UNET SFStab= 0
UNET WFX= 1
UNET SFX= 1
UNET Gravity=32.174
UNET 1D Methodology=Finite Difference
UNET DSS MLevel= 1
UNET Pardiso=0
UNET DZMax Abort= 0
UNET Use Existing IB Tables= 0
UNET Froude Reduction=False
UNET Froude Limit= 0
UNET Froude Power= 0
UNET D1 Cores= 0
UNET WindReference=Eulerian
UNET WindDragFormulation=Hsu (1988)
UNET D2 Coriolis=0
UNET D2 Cores= 0
UNET D2 Theta= 1
UNET D2 Theta Warmup= 1
UNET D2 Z Tol= 0.01
UNET D2 Volume Tol= 0.01
UNET D2 Max Iterations= 20
UNET D2 Equation= 0
UNET D2 RampUpFraction=0.1
UNET D2 TimeSlices= 1
UNET D2 Turbulence Formulation=Non-Conservative (original)
UNET D2 Eddy Viscosity=0.3
UNET D2 Transverse Eddy Viscosity=0.1
UNET D2 Smagorinsky Mixing=0
UNET D2 BCVolumeCheck=0
UNET D2 Cores=0
UNET D2 SolverType=PARDISO (Direct)
UNET D2 Minimum Iterations= 2147483647
UNET D2 Maximum Iterations= 2147483647
UNET D2 Restart Number= 10
UNET D2 Relaxation Coeff=1.3
UNET D2 SOR Precondition Iterations= 10
UNET D2 ILUT Maximum Fill= 8
UNET D2 ILUT Tolerance=1E-08
UNET D1D2 MaxIter= 0
UNET D1D2 ZTol=0.01
UNET D1D2 QTol=0.1
UNET D1D2 MinQTol=1
Write IC File= 0
Write IC File at Fixed DateTime=0
Write IC File at Sim End=0
Echo Input=False
Echo Parameters=False
Echo Output=False
Write Detailed= 0
HDF Write Warmup=0
HDF Write Time Slices=0
HDF Flush=0
HDF Compression= 1
HDF Chunk Size= 1
HDF Spatial Parts= 1
HDF Use Max Rows=0
HDF Fixed Rows= 1
Calibration Method= 0
Calibration Iterations= 20
Calibration Max Change=0.05
Calibration Tolerance=0.2
Calibration Maximum=1.5
Calibration Minimum=0.5
Calibration Optimization Method= 1
WQ AD Non Conservative
WQ ULTIMATE=-1
WQ Max Comp Step=1HOUR
WQ Output Interval=15MIN
WQ Output Selected Increments= 0
WQ Output face flow=0
WQ Output face velocity=0
WQ Output face area=0
WQ Output face dispersion=0
WQ Output cell volume=0
WQ Output cell surface area=0
WQ Output cell continuity=0
WQ Output cumulative cell continuity=0
WQ Output face conc=0
WQ Output face dconc_dx=0
WQ Output face courant=0
WQ Output face peclet=0
WQ Output face adv mass=0
WQ Output face disp mass=0
WQ Output cell mass=0
WQ Output cell source sink temp=0
WQ Output nsm pathways=0
WQ Output nsm derived pathways=0
WQ Create Restart=0
WQ Fixed Restart=0
WQ System Summary=0
WQ Write To DSS=0
Sorting and Armoring Iterations= 10
XS Update Threshold= 0.02
Bed Roughness Predictor= 0
Hydraulics Update Threshold= 0.02
Energy Slope Method= 1
Volume Change Method= 1
Sediment Retention Method= 0
Sediment TS Multiplier= 1
Warm Up Method= 0
XS Weighting Method= 0
Number of US Weighted Cross Sections= 1
Number of DS Weighted Cross Sections= 1
Upstream XS Weight=0
Main XS Weight=1
Downstream XS Weight=0
Number of DS XS's Weighted with US Boundary= 1
Upstream Boundary Weight= 1
Weight of XSs Associated with US Boundary= 0
Number of US XS's Weighted with DS Boundary= 1
Downstream Boundary Weight= 0.5
Weight of XSs Associated with DS Boundary= 0.5
Percentile Method= 0
Sediment Output Level= 3
Mass or Volume Output= 0
Output Increment Type= 1
Profile and TS Output Increment= 1
Transport Output Increment 1
XS Output Flag= 0
XS Output Increment= 10
Read HDF5 Sediment Hotstart= 0
Sediment Hotstart Type= 0
Write Gradation File= 0
Read Gradation Hotstart= 0
Write HDF5 File= 1
Write Binary Output= 1
Write DSS Sediment File= 0
DSS Sediment Output Type= 1
SV Curve= 0
Specific Gage Flag= 0
Subcell Erosion Methods= 0
Subcell Deposition Methods= 0
Advection Scheme= 1
Matrix Solver= 0
Implicit Weighting Factor= 1
Maximum Outer Loop Convergence Iterations= 5
Convergence Maximum Absolute= 0.001
Convergence RMSE= 0.0001
Grain Fractions Max Abs Error= 0.001
Max Subgrid Regions= 1
Max Subgrid Length Scale= 3.402823E+38
Initial Layer Thickness= 3.402823E+38
Min Layer Thickness= 3.402823E+38
Max Layer Thickness= 3.402823E+38
Number of Layers= 5

--- ROSERN.f01 (steady flow) ---

Flow Title=Flow
Program Version=6.20
Number of Profiles= 1
Profile Names=P100yr
River Rch & RM=ROSERN,Main            ,6624
     376
River Rch & RM=ROSERN,Main            ,4773
     418
River Rch & RM=ROSERN,Main            ,2916
     467
River Rch & RM=ROSERN,Main            ,0
     715
Boundary for River Rch & Prof#=ROSERN,Main            , 1
Up Type= 0
Dn Type= 1
Dn Known WS=3038.4
DSS Import GetInterval= 0
DSS Import GetPeak= 0
DSS Import FillOption= 0

--- ROSERN.g01 (geometry) ---

Geom Title=Geometry
Program Version=6.20

River Reach=ROSERN          ,Main
Reach XY= 30
2308672.51835552 643824.662707642308800.12678975643800.100356078
2308872.64568461643740.9749621062308943.11459232643764.779888676
2309095.49162042643476.7927086342309206.42900002643415.722000003
2309502.95700002643359.1250000152309764.06799999643160.861000001
2309919.27600004643085.5140000132310108.16500002643057.388999999
2310367.86600004643178.0380000032310461.87600003 643186.89200002
2310448.59500003643412.673000008     2310744.689643728.819000021
2310879.06400003643814.4960000072311051.39199212643858.257031515
2311146.20505516643974.5904485862311218.99888974 643987.58111029
2311564.39399999644344.965000004     2311765.088644433.854000002
2311878.63000003644446.701000005     2312262.484644668.645000011
2312406.49400005644797.812000006     2312528.109644823.072000012
2312756.49400003645003.541000009     2313283.903645132.122000009
2313466.19500001645297.0520000012313469.50107874645424.829999998
2313625.22200003645644.6219999942313708.15725239 645707.27085115

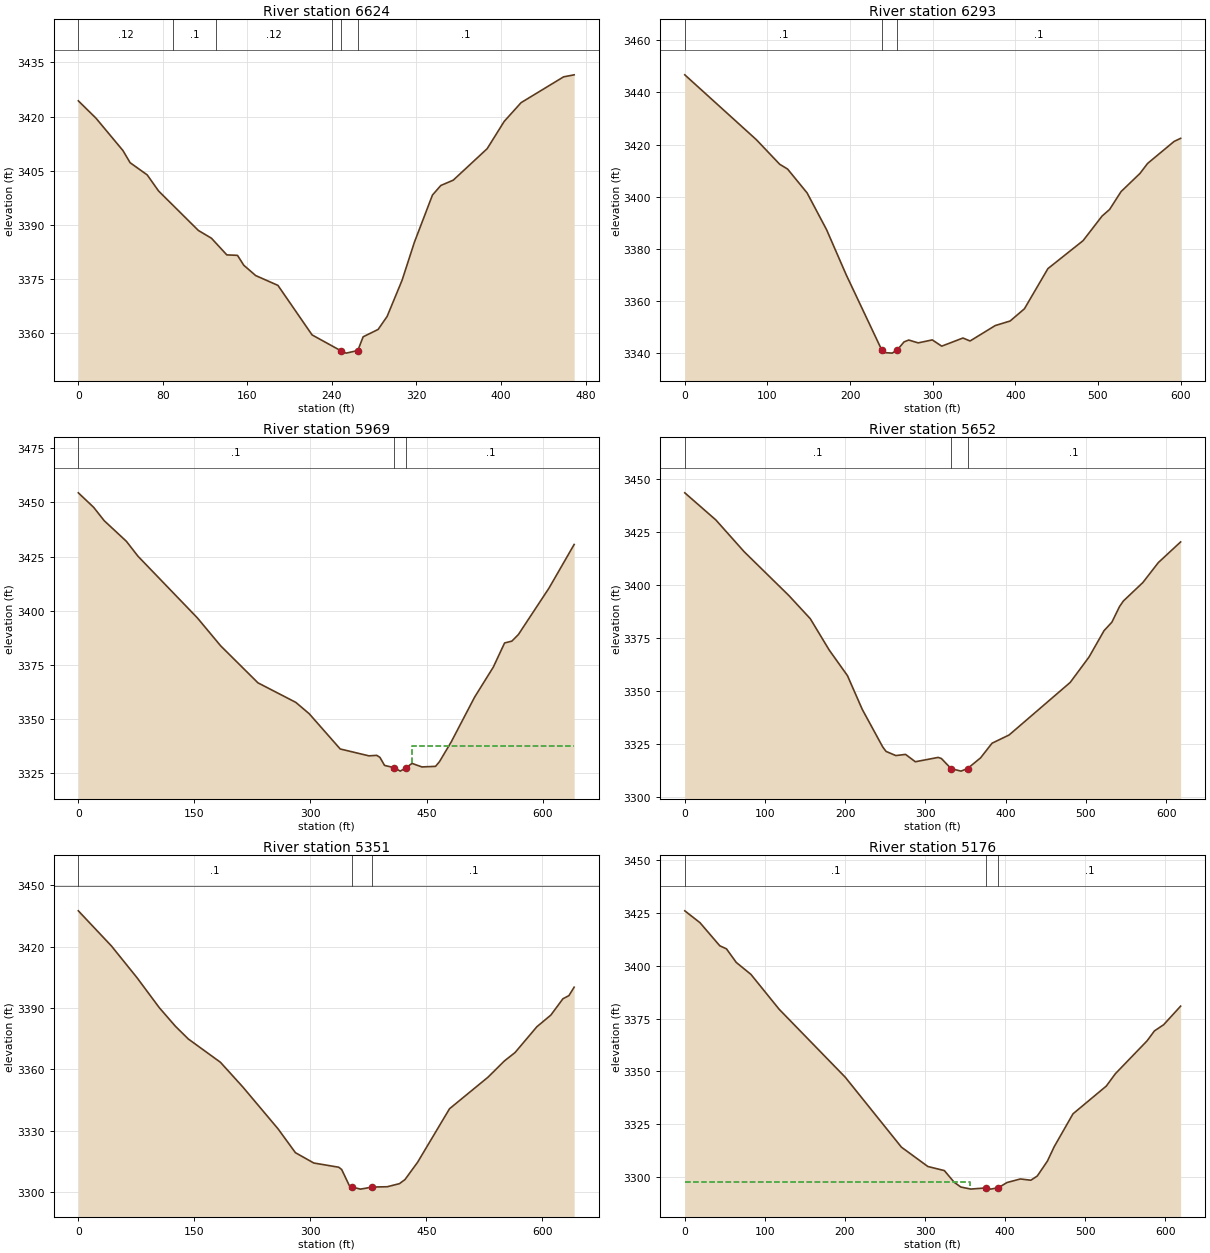
Type RM Length L Ch R = 1 ,6624    ,330.2,331.1,326.4
XS GIS Cut Line= 3
2308864.39717317644005.6301876292308641.52596638643757.764079144
2308506.13691553643745.787355415
#Sta/Elev= 30
       0 3424.35    16.7 3419.54    42.2 3410.57      49  3407.2    65.2 3403.81
    75.9 3399.37   113.6 3388.41     126 3386.25   140.5 3381.64   150.6 3381.51
   156.6 3378.76   167.8 3375.91   188.9 3373.18   221.2 3359.45   248.1 3355.11
   253.4  3354.4  264.48 3355.12   269.5 3358.92   283.7 3360.97   292.2 3364.57
   306.4 3374.64     318 3385.13   335.1 3398.22     343 3400.88   354.8 3402.36
   386.9 3411.09     403 3418.65     419 3423.85   459.2    3431   469.2 3431.56
#Mann= 6 ,-1,0
       0     .12       0      90      .1       0     130     .12       0
     240      .1       0   248.1    .045       0  264.48      .1       0
Bank Sta=248.1,264.48
XS Rating Curve= 0 ,0
Exp/Cntr(USF)=0,0
Exp/Cntr=0.3,0.1

Type RM Length L Ch R = 1 ,6293    ,321.5,323,324.6
XS GIS Cut Line= 4
2309117.75284841643934.5916834462309008.65138672643760.342374398
2308847.39180549643637.3801035962308753.53928335643470.306119442
#Sta/Elev= 30
       0 3446.79    86.6 3421.86   114.9  3412.4   124.4 3410.57     148  3401.4
   171.6 3387.25   195.2 3370.02  238.33 3341.03   241.4 3340.03     251 3339.82
     257 3341.02   265.3 3344.13     271 3344.85   282.4 3343.76   299.5  3344.9
   310.9  3342.5   336.6 3345.63   345.2 3344.49   375.7 3350.42   393.7 3352.17
     411 3356.87   439.4  3372.3     482 3383.06   504.9 3392.49   514.1 3395.06
   527.9  3401.9   550.8 3408.89     560 3412.72   592.1 3421.19     600 3422.38
#Mann= 3 ,-1,0
       0      .1       0  238.33    .045       0     257      .1       0
Bank Sta=238.33,257
XS Rating Curve= 0 ,0
Exp/Cntr=0.3,0.1

Type RM Length L Ch R = 1 ,5969    ,313.3,317.1,321
XS GIS Cut Line= 4
2309363.36164649643804.743444562 2309181.2781665643539.942449603
2309084.22684841643414.9041810392308975.44442474643296.125035898
#Sta/Elev= 30
       0 3454.43    19.7 3447.78    33.5 3441.55    62.1 3432.07    77.1 3425.18
   153.9 3396.71   183.9 3383.86   232.1 3366.78     281 3357.77   298.3 3352.54
   338.4 3336.27   375.5  3333.1   385.6 3333.33   389.7 3332.41   395.7 3328.69
     408 3327.65     416 3326.05   423.9  3327.7   431.2 3329.62   443.9 3327.99
   461.6 3328.25   466.7 3330.44     482 3339.63     512 3360.14   536.2 3374.02
   550.8 3385.17   560.2 3386.02   568.6 3389.03   608.3 3410.54   640.7 3430.61
#Mann= 3 ,-1,0
       0      .1       0     408    .045       0   423.9      .1       0
#XS Ineff= 2 , 0
                          431.12         3337.86
Permanent Ineff=
       F       F
Bank Sta=408,423.9
XS Rating Curve= 0 ,0
Exp/Cntr=0.3,0.1

Type RM Length L Ch R = 1 ,5652    ,304.5,301.2,294.7
XS GIS Cut Line= 4
2309555.43875784643694.5435272732309442.41107921643490.574038246
2309417.72687353643352.8621539352309280.01498922643150.191833628
#Sta/Elev= 30
       0 3443.64    38.7 3430.82      74 3415.79   129.6 3395.11   156.4 3384.12
     180  3369.3   202.8 3357.16   221.2 3341.24   246.8 3323.41   250.9 3321.33
   263.1 3319.37   275.2 3319.92   287.4 3316.45   315.9  3318.5   319.9 3317.97
  331.92 3313.21   344.3 3312.01   352.5 3313.24   368.7 3318.28     383 3325.21
   404.3 3329.11   480.5 3353.98     504 3366.03   522.6 3378.43   532.4 3382.45
     542 3389.89   546.8 3392.51     571  3401.2   590.3 3410.64   618.1 3420.42
#Mann= 3 ,-1,0
       0      .1       0  331.92    .045       0   352.5      .1       0
Bank Sta=331.92,352.5
XS Rating Curve= 0 ,0
Exp/Cntr(USF)=0,0
Exp/Cntr=0.3,0.1

Type RM Length L Ch R = 1 ,5351    ,171.9,175.4,178.7
XS GIS Cut Line= 3
2309799.56335833643562.470527046 2309728.3458436643301.216003753
 2309507.4547488643003.737439749
#Sta/Elev= 30
       0 3437.46    42.8 3420.28      76  3404.7   104.8 3390.04   125.7 3380.94
   142.3 3374.76   183.8 3363.38   212.8 3351.28   258.4 3330.78   280.8 3319.15
   304.6  3314.1   336.7 3312.05   340.6 3310.94   350.5 3303.06   353.9 3302.36
     365 3301.33   380.4 3302.35   399.6  3302.5   415.3    3304   422.5 3306.01
   438.8 3314.47   480.1 3340.65   529.9 3356.09   551.1 3364.04   564.8 3368.12
   593.1 3380.77   611.2 3386.48   626.7 3394.42   634.5 3395.98   641.3 3400.11
#Mann= 3 ,-1,0
       0      .1       0   353.9    .045       0   380.4      .1       0
Bank Sta=353.9,380.4
XS Rating Curve= 0 ,0
Exp/Cntr=0.3,0.1

Type RM Length L Ch R = 1 ,5176    ,208.7,210.8,212.1
XS GIS Cut Line= 3
2309913.91235755643507.585871526 2309807.4774895643082.635060193
2309681.45812367642952.718188202
#Sta/Elev= 30
       0 3425.98      19 3420.35    43.7 3409.43      52    3408    64.3 3401.54
    82.6 3395.89   117.9 3379.36   200.4 3347.21   270.5 3314.12   303.5 3304.97
   324.1 3303.04   336.4 3297.49   344.7 3295.25   357.1 3294.29     376 3294.83
   381.8 3294.26   391.5 3294.93   402.4  3297.4     419 3299.07   432.1 3298.47
   440.1 3300.46   452.8 3307.55   461.2 3314.31   484.7  3329.9   526.3 3343.04
   537.6 3348.87   577.2 3364.44   586.4 3369.15   597.9 3372.07   619.1 3380.87
#Mann= 3 ,-1,0
       0      .1       0     376    .045       0   391.5      .1       0
#XS Ineff= 2 , 0
          356.39 3297.59
Permanent Ineff=
       F       F
Bank Sta=376,391.5
XS Rating Curve= 0 ,0
Exp/Cntr(USF)=0,0
Exp/Cntr=0.3,0.1

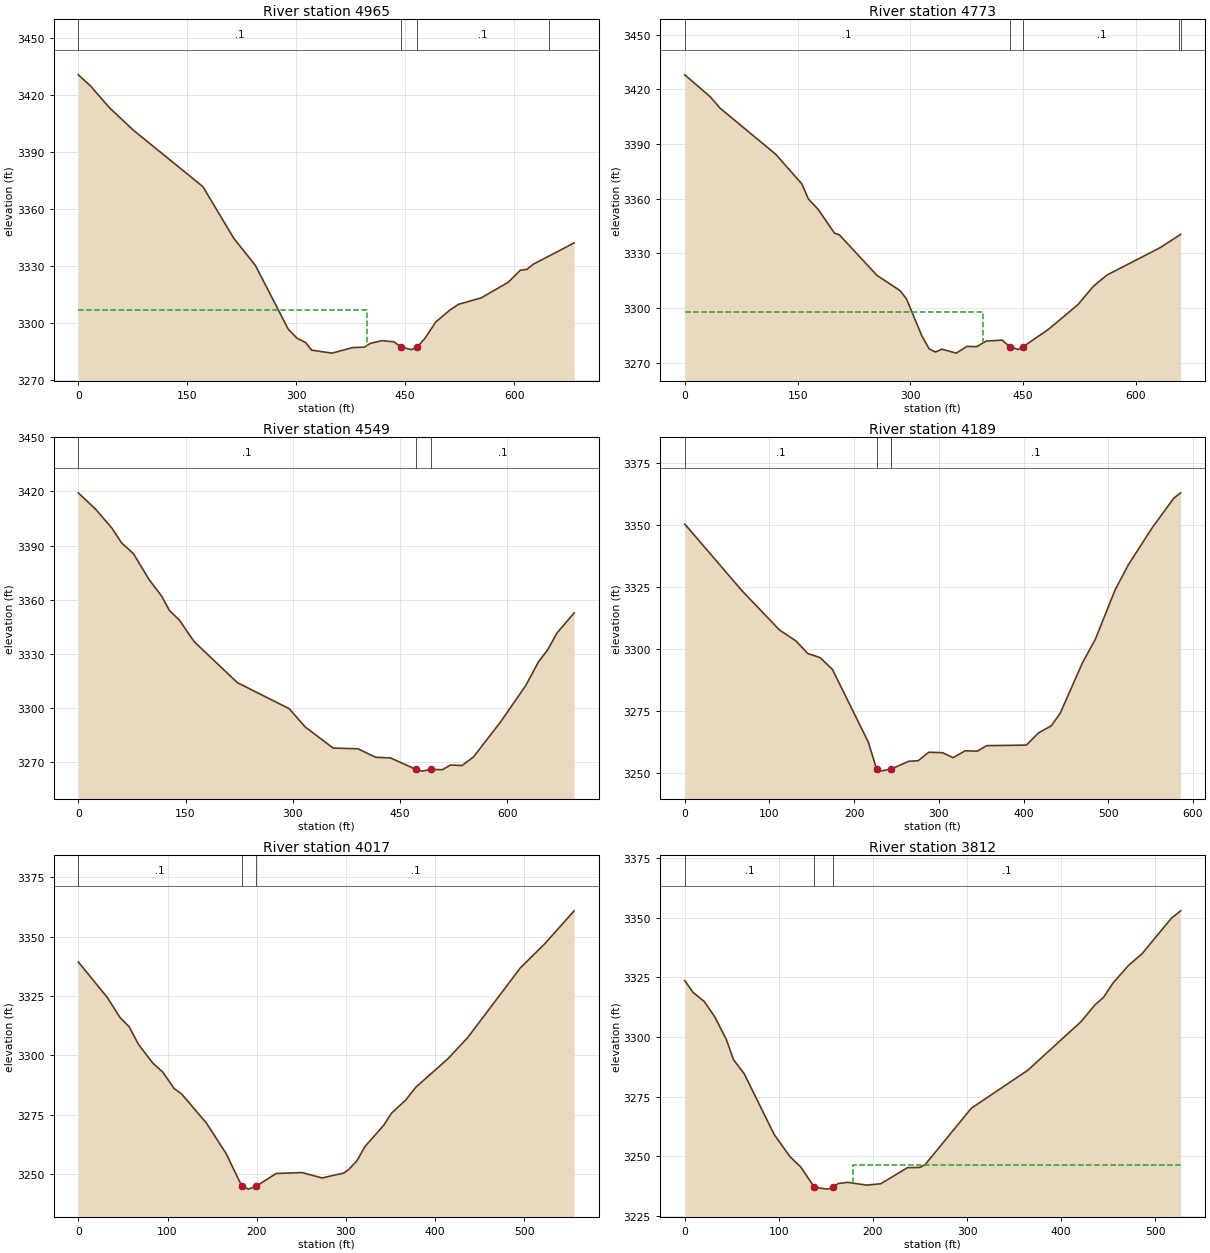
Type RM Length L Ch R = 1 ,4965    ,185.9,191.6,195.7
XS GIS Cut Line= 4
2309973.77108565643515.2582439242310036.13118421643234.637800423
2310011.44697853643046.2583360352310103.68795764642863.075546528
#Sta/Elev= 30
       0 3430.62    17.2 3424.61    43.1 3413.21    75.9 3401.43   171.4 3371.79
   213.9 3344.63   243.9 3330.19   288.9 3296.78     301 3291.99   313.1 3289.61
   321.2 3285.66   349.4  3284.1   377.7 3287.03   393.8 3287.25   401.9 3289.22
     418 3290.66   434.2 3290.07  444.743287.278   458.4 3285.95   466.4 3287.26
   477.5 3292.05   492.1  3300.5   511.6 3306.81   523.4 3309.79   554.8 3313.22
     592 3321.46   608.5 3327.77   617.5 3328.18   626.5 3330.94   682.6 3342.14
#Mann= 4 ,-1,0
       0      .1       0  444.74    .045       0   466.4      .1       0
  647.46     .12       0
#XS Ineff= 2 , 0
          397.26 3307.03
Permanent Ineff=
       F       F
Bank Sta=444.74,466.4
XS Rating Curve= 0 ,0
Exp/Cntr(USF)=0,0
Exp/Cntr=0.3,0.1

Type RM Length L Ch R = 1 ,4773    ,226.1,224.4,219.5
XS GIS Cut Line= 4
2310022.06904064643520.4160470452310145.95590485643229.152205424
2310194.24001742643085.8440069312310284.78726721642917.083251663
#Sta/Elev= 30
       0 3428.05    33.9 3415.97      47 3409.71   120.9 3384.41   155.7 3368.13
   164.3 3359.88   177.4 3354.11   199.1 3341.06   205.4 3340.21   255.6 3317.87
   286.1 3309.56   294.8 3304.97   315.1 3284.78   324.9 3277.51   333.4 3275.79
   341.8 3277.35     361 3275.18   375.1 3278.88   388.2 3278.72   400.9 3281.82
     422 3282.32   431.9 3278.73   443.1 3277.13  450.163278.753   484.4 3288.52
   522.6 3301.77   543.5 3311.98   561.2 3318.04   631.9 3333.06   659.3 3340.41
#Mann= 5 ,-1,0
       0      .1       0   431.9    .045       0  450.16      .1       0
  657.74     .12       0  659.26      .1       0
#XS Ineff= 2 , 0
          396.25 3297.55
Permanent Ineff=
       F       F
Bank Sta=431.9,450.16
XS Rating Curve= 0 ,0
Exp/Cntr=0.3,0.1

Type RM Length L Ch R = 1 ,4549    ,354.6,359.6,369.3
XS GIS Cut Line= 4
2310091.16397118 643540.514083842310389.97277676 643233.91026594
2310392.83798675643101.7391552322310445.83703172642979.273196837
#Sta/Elev= 30
       0 3419.26    24.4  3410.1    47.3 3399.53    60.5 3391.54    77.3 3385.46
    99.2  3371.1   116.4 3362.16   127.5 3354.09   141.7 3348.63   161.9 3336.89
   222.5 3314.13   295.1 3299.68   317.4 3289.59   356.5 3277.88   391.2 3277.49
   416.1 3272.77   436.9 3272.42  472.573266.031   480.9  3265.1   493.7 3266.05
   509.3  3265.9   520.9 3268.51   536.9  3268.2   552.9 3272.94   590.7 3292.29
   626.3 3312.65   643.8 3325.58   656.8 3332.34   669.9 3341.68   693.8 3352.77
#Mann= 3 ,-1,0
       0      .1       0  472.57    .045       0   493.7      .1       0
Bank Sta=472.57,493.7
XS Rating Curve= 0 ,0
Exp/Cntr(USF)=0,0
Exp/Cntr=0.3,0.1

Type RM Length L Ch R = 1 ,4189    ,169.5,172.4,174.1
XS GIS Cut Line= 3
2310357.33056294643643.2605886432310594.70690895643275.873864486
2310699.82664273643171.528913764
#Sta/Elev= 30
       0 3350.33    67.2 3323.58     112 3307.58   131.1 3303.28   145.3 3298.15
   159.8  3296.5   174.3 3291.77   216.8 3262.39   226.4 3251.65   231.1 3250.75
   243.7 3251.61   264.4 3254.72   275.5 3254.94   288.2 3258.36   304.4 3258.19
   316.8 3256.16   331.1 3258.95   345.4 3258.81   356.5 3261.02   403.3 3261.24
     418 3266.23   432.7    3269   443.2 3274.01   469.6 3294.43   484.6 3303.76
   508.2 3323.86     524 3334.04   552.2 3348.98   577.5 3360.78   585.5 3362.92
#Mann= 3 ,-1,0
       0      .1       0   226.4    .045       0   243.7      .1       0
Bank Sta=226.4,243.7
XS Rating Curve= 0 ,0
Exp/Cntr=0.3,0.1

Type RM Length L Ch R = 1 ,4017    ,205,204.7,203.8
XS GIS Cut Line= 2
2310453.63204404 643696.414330232310869.36603441643327.450413774
#Sta/Elev= 30
       0 3339.35    32.4 3324.44    46.6    3316    56.9  3312.1    67.6 3304.54
    83.4 3296.78    94.8 3292.89   107.3 3286.05   115.7 3283.78   143.5  3271.5
   165.6 3258.67  183.293244.863   190.6 3243.63   199.6 3244.93   221.8 3250.21
   250.6 3250.61   273.3 3248.35   297.5 3250.39   302.9 3251.86   312.2 3255.51
   321.4 3261.62   342.3 3270.53     351 3275.63   366.8  3281.1   378.5 3286.63
   414.6 3298.68   436.6 3307.56   495.4 3336.82   523.1 3347.11   555.8  3360.9
#Mann= 3 ,-1,0
       0      .1       0  183.29    .045       0   199.6      .1       0
Bank Sta=183.29,199.6
XS Rating Curve= 0 ,0
Exp/Cntr(USF)=0,0
Exp/Cntr=0.3,0.1

Type RM Length L Ch R = 1 ,3812    ,165.9,161.7,157.9
XS GIS Cut Line= 2
2310629.05759615643823.2814247372311001.19744456643450.163979114
#Sta/Elev= 30
       0 3323.64     8.6 3318.75    20.7 3314.88      32 3308.33    44.1 3298.99
    51.8 3290.46    63.1  3284.6      95 3259.09     112 3249.69   123.4  3245.4
  137.673236.933   151.7 3236.16  157.77 3236.93     163 3238.51   173.4    3239
   193.2 3237.84   208.3 3238.41   236.7 3245.16   249.8 3245.27   255.4 3246.43
   304.6 3270.12   364.5 3286.02     421 3306.37   436.4 3313.66   444.9 3316.52
   454.9 3322.51   471.9 3330.14   485.9 3334.86   517.1 3349.79     527 3352.92
#Mann= 3 ,-1,0
       0      .1       0  137.67    .045       0  157.77      .1       0
#XS Ineff= 2 , 0
                          178.34         3246.39
Permanent Ineff=
       F       F
Bank Sta=137.67,157.77
XS Rating Curve= 0 ,0
Exp/Cntr=0.3,0.1

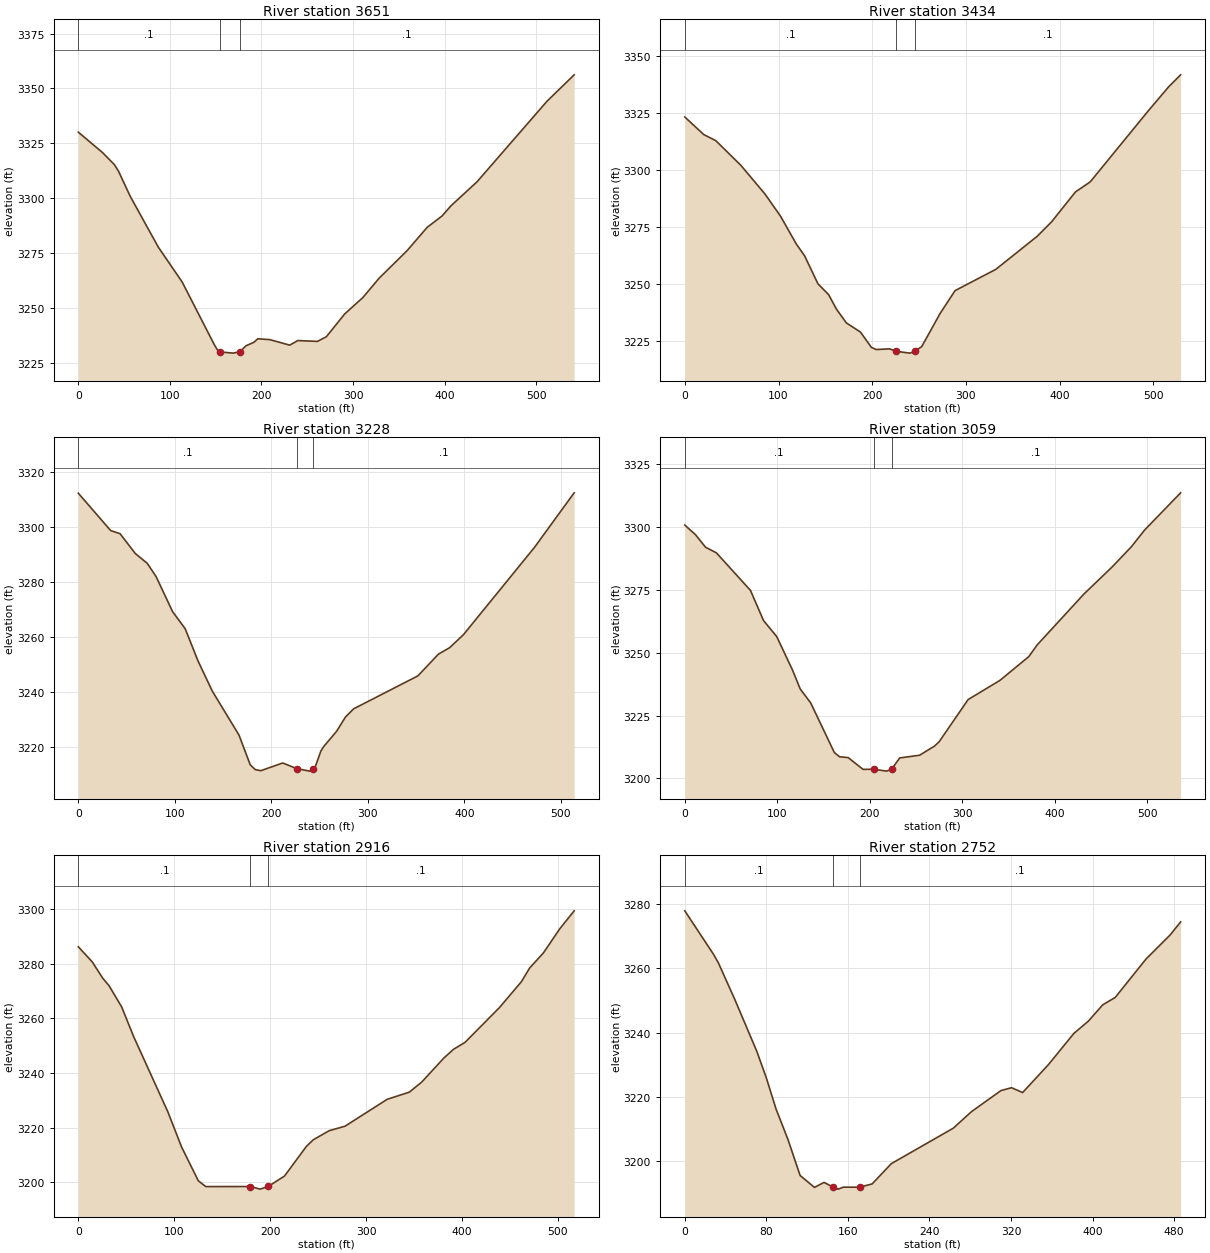
Type RM Length L Ch R = 1 ,3651    ,214.6,216.3,220.5
XS GIS Cut Line= 3
2310801.80926098643961.4447490922310912.23860217643702.910173829
2311087.62637936643510.633203282
#Sta/Elev= 30
       0  3330.1    26.4 3320.81    39.4 3315.29    43.8 3312.38    56.8 3300.78
    87.3 3277.77   113.4 3261.86   148.3 3233.47   152.5 3230.49   154.4 3230.06
     169 3229.49  176.423230.126     183 3232.82   191.7 3234.42     196 3236.02
   209.1 3235.63   230.8 3233.13   239.7 3235.21   261.1 3234.83   270.8 3236.94
   290.8 3247.31   310.7  3254.8   328.5 3263.63   358.8 3276.06   380.9 3286.75
   397.2 3291.95   406.9 3296.57   435.4 3307.52   511.7 3344.15   541.4  3356.2
#Mann= 3 ,-1,0
       0      .1       0   154.4    .045       0  176.42      .1       0
Bank Sta=154.4,176.42
XS Rating Curve= 0 ,0
Exp/Cntr(USF)=0,0
Exp/Cntr=0.3,0.1

Type RM Length L Ch R = 1 ,3434    ,204,205.9,204.7
XS GIS Cut Line= 2
2310912.23860217644045.8907158862311264.31332527643650.943425033
#Sta/Elev= 30
       0 3323.17    20.3 3315.45    33.1 3312.81    59.9 3301.99    85.5 3289.51
   102.1 3279.82   118.8 3267.74   127.9  3262.4   142.1  3250.2   153.4 3245.51
   161.9 3239.08   172.4 3233.11   187.4 3229.12   199.2 3222.38   204.3 3221.47
   218.6 3221.75  225.443220.682   240.4 3219.89  245.313220.697   252.8 3222.73
   272.4 3237.21   288.4 3247.22   331.9 3256.53   376.1    3271   391.4 3277.31
   416.9 3290.39   432.7 3294.81   493.4 3325.26   516.1 3336.25   529.1  3341.6
#Mann= 3 ,-1,0
       0      .1       0  225.44    .045       0  245.31      .1       0
Bank Sta=225.44,245.31
XS Rating Curve= 0 ,0
Exp/Cntr(USF)=0,0
Exp/Cntr=0.3,0.1

Type RM Length L Ch R = 1 ,3228    ,168.4,169.6,169.2
XS GIS Cut Line= 3
2311051.61363417644156.0431392672311237.03078215643967.940592692
2311398.81728816643777.810307987
#Sta/Elev= 30
       0 3312.35    33.5 3298.79    43.3 3297.64      59 3290.46    71.4 3286.89
    80.6 3282.06    97.7 3269.32   110.7 3263.15     124 3251.46   138.8 3240.49
   166.5  3224.5   178.1 3213.74   183.4 3211.95   189.1 3211.57   211.8 3214.37
   226.5 3212.31   239.9 3211.41  243.633212.312   245.7 3213.15   251.3 3218.68
   254.2 3220.31   267.8 3225.95   276.8 3231.06   285.3 3234.04   351.8 3245.99
   373.3 3253.94   384.7 3256.22   399.1 3260.98   472.7 3292.68   513.8 3312.49
#Mann= 3 ,-1,0
       0      .1       0   226.5    .045       0  243.63      .1       0
Bank Sta=226.5,243.63
XS Rating Curve= 0 ,0
Exp/Cntr=0.3,0.1

Type RM Length L Ch R = 1 ,3059    ,143,142.4,141.6
XS GIS Cut Line= 3
2311166.87567127644260.2535546722311359.15264182644084.865777484
2311528.04457541643866.605432538
#Sta/Elev= 30
       0 3300.76    11.6 3296.94    22.4 3291.97    34.2 3289.72      71 3274.79
    85.2 3262.75    99.4 3256.43   116.4 3243.17   124.8 3235.59   136.2 3229.98
   161.7  3210.3   167.3  3208.6   176.7 3208.26   192.8 3203.57   204.1 3203.64
   218.3 3202.88   223.7 3203.67   232.4 3208.13   253.9  3209.2     270 3212.83
     275 3214.53   306.4 3231.35   340.8 3238.98     372 3248.44   381.2 3253.14
   431.8  3273.4   462.2 3284.13   483.2 3292.26   497.2 3298.78   536.2  3313.6
#Mann= 3 ,-1,0
       0      .1       0   204.1    .045       0   223.7      .1       0
Bank Sta=204.1,223.7
XS Rating Curve= 0 ,0
Exp/Cntr(USF)=0,0
Exp/Cntr=0.3,0.1

Type RM Length L Ch R = 1 ,2916    ,168.2,164.3,162.7
XS GIS Cut Line= 3
2311294.19420582644355.0928712262311544.93376877644090.062452364
2311637.17474788643969.239761412
#Sta/Elev= 30
       0 3286.23    14.5 3280.69    25.4 3274.74      32 3271.98    45.2 3264.19
    57.7  3253.3    93.3  3225.8   107.6 3212.93   125.1 3200.52   132.9  3198.4
  179.413198.425   189.5 3197.47     198 3198.44     215 3202.28   237.6 3213.06
   244.9 3215.54   261.4 3218.85     278 3220.51     322 3230.36   345.1 3232.99
   357.9 3236.65   381.1 3245.49   391.1 3248.67   403.1 3251.21   439.1 3263.99
     462 3273.48   470.5 3278.45   484.8 3283.96     502 3292.85   516.9 3299.39
#Mann= 3 ,-1,0
       0      .1       0  179.41    .045       0     198      .1       0
Bank Sta=179.41,198
XS Rating Curve= 0 ,0
Exp/Cntr(USF)=0,0
Exp/Cntr=0.3,0.1

Type RM Length L Ch R = 1 ,2752    ,200.4,198.7,199.3
XS GIS Cut Line= 2
2311456.89944345644469.1513447932311714.10905394644056.377687528
#Sta/Elev= 30
       0 3277.77    28.2 3264.27      33 3261.58    48.8 3250.45    70.7 3234.13
    80.1 3225.82    89.5 3216.28   101.1 3206.91   113.1 3195.66   127.2 3191.94
   136.6  3193.5  145.743191.996   150.4 3191.41   155.5 3192.02  171.56 3192.01
   183.8 3193.03   202.6 3199.32   263.4 3210.32   281.1 3215.42   310.1 3221.98
   320.5 3222.88   331.4 3221.38   356.6    3230   381.7 3239.74   395.9 3243.54
     410  3248.6   422.2 3250.88   452.4 3262.79     476 3270.24   486.4 3274.33
#Mann= 3 ,-1,0
       0      .1       0  145.74    .045       0  171.56      .1       0
Bank Sta=145.74,171.56
XS Rating Curve= 0 ,0
Exp/Cntr(USF)=0,0
Exp/Cntr=0.3,0.1

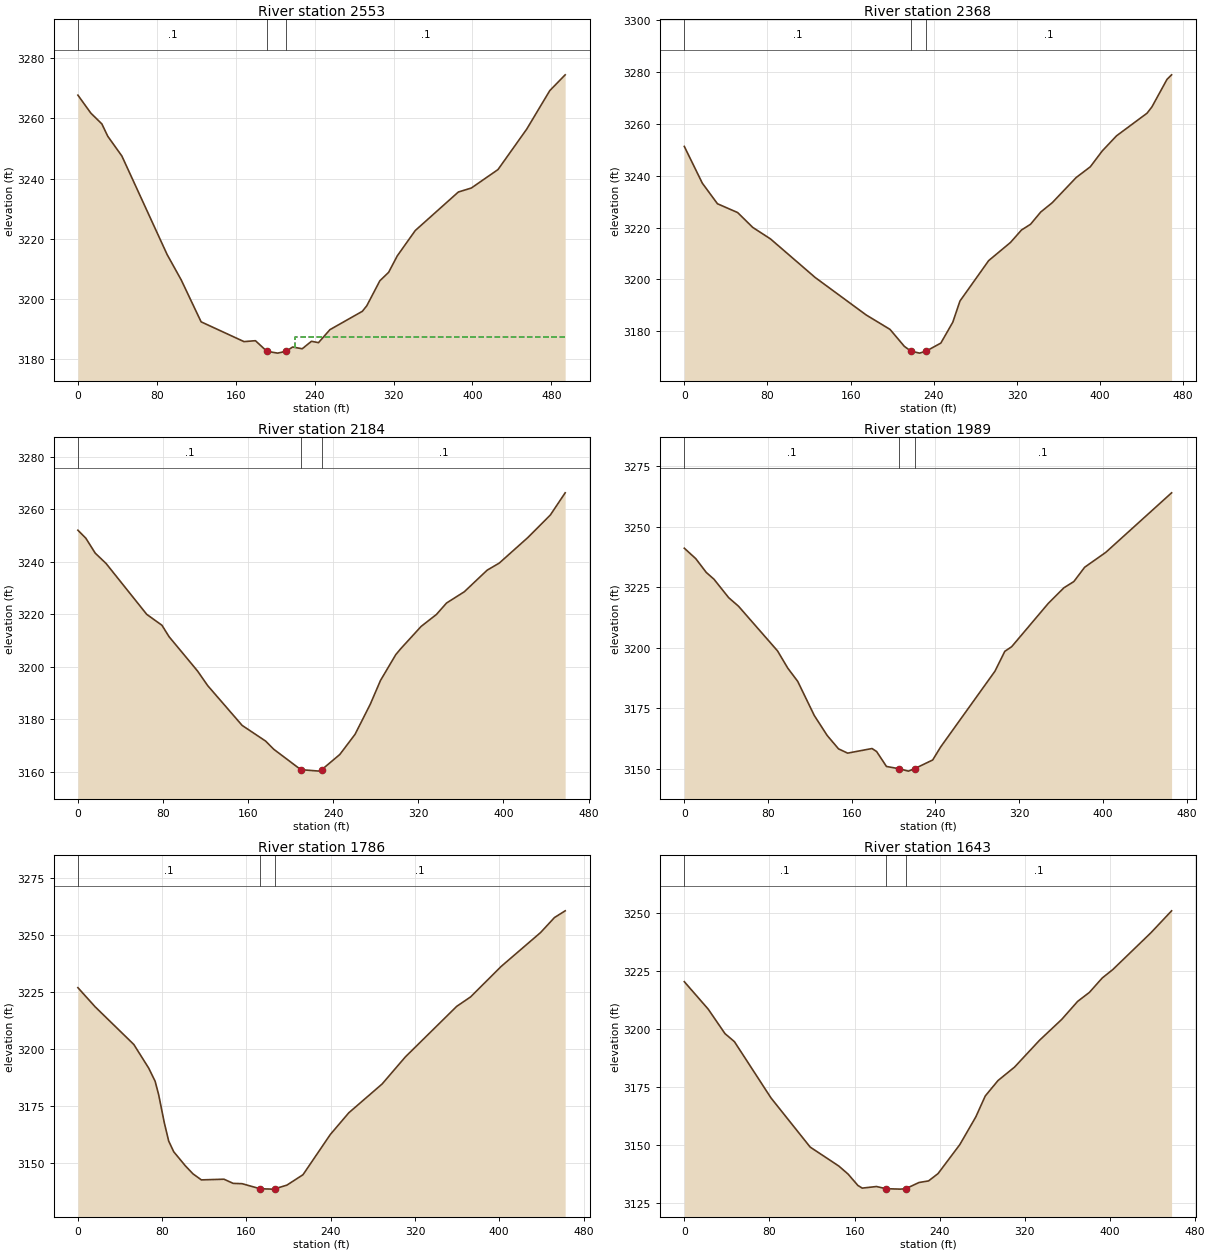
Type RM Length L Ch R = 1 ,2553    ,184.4,185.1,183.1
XS GIS Cut Line= 4
2311609.89220476644577.2507223322311678.74814692644482.411405778
2311767.09161987644342.1011840272311856.73426155  644151.1233822
#Sta/Elev= 30
       0 3267.69    13.1 3261.73    24.3 3258.14    30.3 3254.04    44.6 3247.48
    90.5 3214.78   104.8 3206.35   124.9 3192.48   168.4 3185.92     180 3186.22
   191.6 3182.71   202.5  3182.1  211.183182.719   217.7 3184.13   227.4 3183.55
   236.8 3186.03   243.9 3185.57   255.5 3189.88   288.4 3195.98   292.9 3197.83
   306.1 3206.09     315  3208.9   323.8 3214.37     342 3222.77   385.7 3235.55
   398.9 3236.88   425.9    3243     455 3256.41   478.4 3269.19     494 3274.43
#Mann= 3 ,-1,0
       0      .1       0   191.6    .045       0  211.18      .1       0
#XS Ineff= 2 , 0
                          220.58         3187.46
Permanent Ineff=
       F       F
Bank Sta=191.6,211.18
XS Rating Curve= 0 ,0
Exp/Cntr(USF)=0,0
Exp/Cntr=0.3,0.1

Type RM Length L Ch R = 1 ,2368    ,184.2,184.3,184.3
XS GIS Cut Line= 2
2311767.09161987644647.4058332072312033.42120746644261.552723392
#Sta/Elev= 30
       0 3251.29    17.3 3237.13    31.9 3229.17    51.3 3225.78    65.9 3220.03
    82.9 3215.61     126  3200.7   174.9 3186.29   197.9 3180.71   211.7 3174.16
     218 3172.33   226.3 3171.55   232.4 3172.27   246.8 3175.42   258.3 3183.48
   265.2 3191.65   292.8 3207.23   313.8 3214.24   324.4 3219.05   333.1 3221.26
   342.9 3225.98     354 3229.58     377 3239.29   390.6 3243.43   402.1 3249.55
   415.8 3255.37   445.2 3264.11   449.9 3266.55   464.4 3277.17   468.8 3278.91
#Mann= 3 ,-1,0
       0      .1       0     218    .045       0   232.4      .1       0
Bank Sta=218,232.4
XS Rating Curve= 0 ,0
Exp/Cntr(USF)=0,0
Exp/Cntr=0.3,0.1

Type RM Length L Ch R = 1 ,2184    ,194.9,195.3,194.6
XS GIS Cut Line= 2
2311935.77897148644735.3758015152312186.07720394644351.803689893
#Sta/Elev= 30
       0 3252.08     7.4 3249.07    16.3 3243.34    26.5  3239.4    64.7 3220.02
      79 3215.86    85.7  3211.5   112.5 3198.41     122 3192.86   154.4 3177.69
   176.4 3171.74   184.1 3168.61  209.57 3160.83   227.1 3160.28  229.093160.791
   246.2 3166.63   260.5 3174.31   274.9 3185.85   284.4 3194.82   298.8 3204.68
   303.5 3206.95   322.6 3215.42     337 3219.98   346.5 3224.34   363.2 3228.63
   384.7 3236.87     396 3239.54   422.9 3249.28   444.1  3257.9     458 3266.33
#Mann= 3 ,-1,0
       0      .1       0  209.57    .045       0  229.09      .1       0
Bank Sta=209.57,229.09
XS Rating Curve= 0 ,0
Exp/Cntr(USF)=0,0
Exp/Cntr=0.3,0.1

Type RM Length L Ch R = 1 ,1989    ,201.3,202.3,203.5
XS GIS Cut Line= 2
2312109.07021615644829.1470181052312355.31920851644433.902221708
#Sta/Elev= 30
       0 3241.12    10.9 3236.83      21 3231.11    28.4 3228.29    42.4  3220.7
    51.8 3217.17    89.1 3198.72    98.9  3191.6   108.4 3186.14   124.2 3172.07
   136.6 3163.78   147.4 3158.28   156.1 3156.52   179.4 3158.42   183.8 3157.18
   193.2 3151.02   205.5 3150.05   214.2 3149.09     220 3150.08   237.4  3153.7
     245 3159.07   296.9 3190.35   306.3 3198.54   312.9 3200.47   347.8 3218.31
   362.8 3224.78   372.3 3227.35   382.6 3233.25   402.8  3239.4   465.7 3263.98
#Mann= 3 ,-1,0
       0      .1       0   205.5    .045       0     220      .1       0
Bank Sta=205.5,220
XS Rating Curve= 0 ,0
Exp/Cntr(USF)=0,0
Exp/Cntr=0.3,0.1

Type RM Length L Ch R = 1 ,1786    ,143.5,143.7,140.3
XS GIS Cut Line= 4
2312267.27157704644917.6329269492312319.23832584644837.084466314
2312397.18844903 644750.040162082312503.72028406644523.984804815
#Sta/Elev= 30
       0  3226.9    16.4  3218.5    53.1 3202.02    67.2 3191.68    73.3 3185.94
    76.7 3179.97      82 3167.81    86.2 3159.73      91 3155.04   102.1 3148.85
   109.3 3145.36   117.2 3142.74   138.7 3143.03   147.4 3141.21   155.9 3141.07
   172.9 3138.86   184.3 3138.69   187.2 3138.87   198.4 3140.43   213.7    3145
   239.6 3162.59   257.2 3172.12   288.8 3184.72   310.9 3196.59   359.6  3218.7
   372.8 3222.85   401.9 3236.22   439.2 3251.01   452.4 3257.58   462.6 3260.54
#Mann= 3 ,-1,0
       0      .1       0   172.9    .045       0   187.2      .1       0
Bank Sta=172.9,187.2
XS Rating Curve= 0 ,0
Exp/Cntr(USF)=0,0
Exp/Cntr=0.3,0.1

Type RM Length L Ch R = 1 ,1643    ,150.1,151.8,150.7
XS GIS Cut Line= 2
2312420.57348599644995.5830501442312620.64546886644583.746565931
#Sta/Elev= 30
       0 3220.36    22.5 3208.51    38.2 3198.01    47.1 3194.53    81.5 3170.27
   118.3 3149.12   145.2 3140.96   153.9  3137.5   163.1 3132.61   167.2 3131.46
   180.6 3132.14   189.4 3131.21   202.8 3131.02     208 3131.19   220.6 3133.88
   229.5 3134.55   238.4 3137.69   258.9  3150.2   273.9  3162.1   282.8 3171.13
   294.8 3177.79   310.3 3183.56   333.7 3195.08   354.7 3204.13   369.6 3211.87
   380.7 3215.76   392.7 3221.94   402.6 3225.56   438.5 3241.44   457.9 3250.88
#Mann= 3 ,-1,0
       0      .1       0   189.4    .045       0     208      .1       0
Bank Sta=189.4,208
XS Rating Curve= 0 ,0
Exp/Cntr(USF)=0,0
Exp/Cntr=0.3,0.1

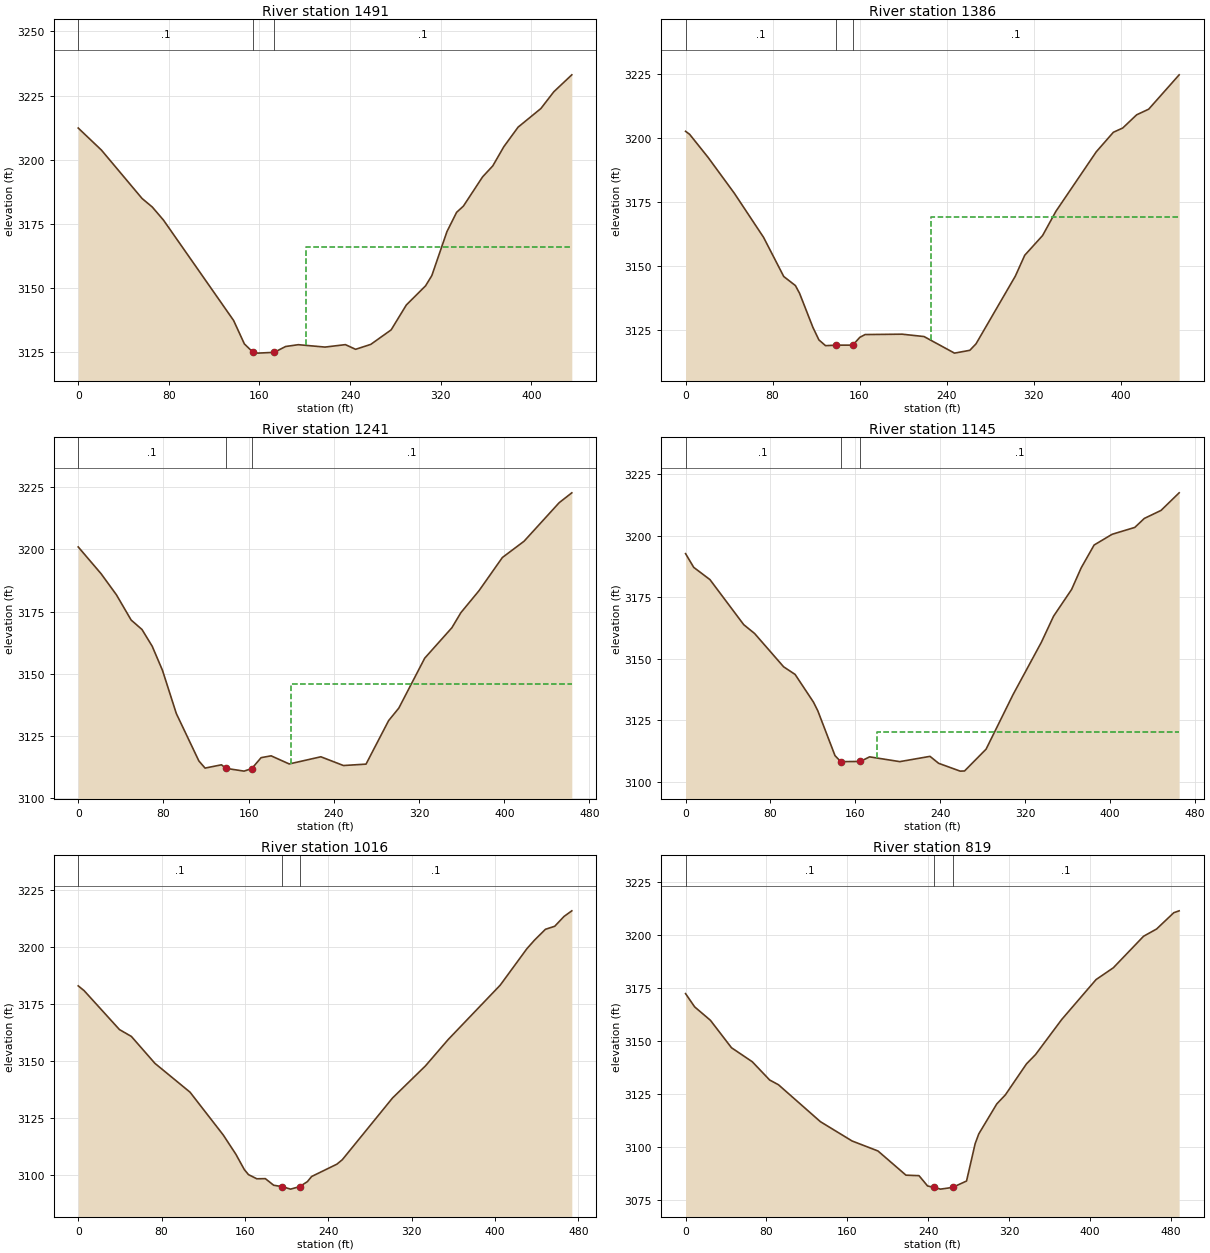
Type RM Length L Ch R = 1 ,1491    ,102.9,104.6,107
XS GIS Cut Line= 2
2312549.19118926  645051.44730512312746.66483469644662.995857846
#Sta/Elev= 30
       0 3212.34    20.5 3203.74    56.4 3184.86    65.4 3181.54    75.3 3176.43
   137.2  3137.3   146.7 3128.17  154.393124.865   158.6 3124.57   173.1 3124.88
   183.1 3127.15   194.3 3127.86   217.9 3126.93   235.9 3127.88   244.9 3126.06
   258.3 3127.98   276.3 3133.64   289.7 3143.35   306.7 3150.82   312.2  3154.8
   325.6    3172   334.1 3179.48   340.1 3181.91     357 3193.29     366 3197.57
   375.8 3205.08   388.4  3212.7   408.5 3219.95   419.9 3226.48   435.8 3233.09
#Mann= 3 ,-1,0
       0      .1       0  154.39    .045       0   173.1      .1       0
#XS Ineff= 2 , 0
                             201         3165.96
Permanent Ineff=
       F       F
Bank Sta=154.39,173.1
XS Rating Curve= 0 ,0
Exp/Cntr(USF)=0,0
Exp/Cntr=0.3,0.1

Type RM Length L Ch R = 1 ,1386    ,148.3,145.8,141.3
XS GIS Cut Line= 3
2312614.14962526645068.3364984592312797.33241477644864.367009433
2312862.29085076644696.774244564
#Sta/Elev= 30
       0 3202.77     3.7 3201.62    20.7 3192.59    44.9 3178.54    71.7 3161.36
    90.3 3146.03     101  3142.5   104.8 3139.51   117.1 3126.16   122.6 3121.27
   128.7 3119.01   138.7  3119.2   153.8 3119.22   160.2 3122.25   165.1 3123.35
   199.1 3123.49   219.3 3122.57   247.3 3116.09   261.4 3117.19   267.1 3119.72
   303.3 3146.22   311.9 3154.34   328.3 3162.03   340.6 3171.53   377.7 3194.78
   393.4  3202.4     402 3204.06   414.8 3209.22   425.9 3211.43   453.9 3224.85
#Mann= 3 ,-1,0
       0      .1       0   138.7    .045       0   153.8      .1       0
#XS Ineff= 2 , 0
                          225.91         3169.26
Permanent Ineff=
       F       F
Bank Sta=138.7,153.8
XS Rating Curve= 0 ,0
Exp/Cntr(USF)=0,0
Exp/Cntr=0.3,0.1

Type RM Length L Ch R = 1 ,1241    ,96.8,95.5,94.8
XS GIS Cut Line= 3
2312769.12238004645155.0575972952312814.24945921645087.036323967
2312941.07478859644726.957715874
#Sta/Elev= 30
       0 3200.99    21.5 3190.22    35.9 3181.75    49.7 3171.63    59.9 3167.82
    69.5 3161.08    79.1 3151.44    92.1 3134.09   113.3 3115.03   119.1 3112.18
   134.5  3113.5   138.7 3112.08   155.7 3110.96     163 3112.01   171.7 3116.37
   181.1  3117.1   198.1 3113.84   227.8 3116.72     249 3113.21   270.2 3113.77
   291.4 3131.23     301 3136.28   325.3 3156.32   350.8 3168.54   359.3 3174.62
   376.3 3183.43   398.2 3196.74   418.6 3203.29   451.5 3218.74   463.4 3222.72
#Mann= 3 ,-1,0
       0      .1       0   138.7    .045       0     163      .1       0
#XS Ineff= 2 , 0
                          199.34         3145.96
Permanent Ineff=
       F       F
Bank Sta=138.7,163
XS Rating Curve= 0 ,0
Exp/Cntr(USF)=0,0
Exp/Cntr=0.3,0.1

Type RM Length L Ch R = 1 ,1145    ,129.1,129.1,128.4
XS GIS Cut Line= 4
2312854.84992214645199.6692820722312915.03959343645107.138891893
2312946.48195902644934.655057772 2313006.6716303644765.764636862
#Sta/Elev= 30
       0 3192.78     7.7 3187.21      23 3182.22    54.8 3163.92      65 3160.35
    92.4 3146.79   103.2  3143.7   120.5 3132.44   124.6  3128.9   140.8 3110.69
   146.2 3108.26   164.6 3108.33   173.4  3110.2   201.8 3108.26   230.3  3110.4
   238.4 3107.58   258.7  3104.4   262.8 3104.46   283.1 3113.32   308.5 3135.48
   335.2 3156.77   346.7 3167.37   363.7 3178.25   372.7 3187.01   384.9 3196.29
   401.9 3200.66   423.2 3203.44   432.2  3207.1   447.9 3210.34     465  3217.5
#Mann= 3 ,-1,0
       0      .1       0   146.2    .045       0   164.6      .1       0
#XS Ineff= 2 , 0
                          180.51         3120.48
Permanent Ineff=
       F       F
Bank Sta=146.2,164.6
XS Rating Curve= 0 ,0
Exp/Cntr(USF)=0,0
Exp/Cntr=0.3,0.1

Type RM Length L Ch R = 1 ,1016    ,194.4,197,198.4
XS GIS Cut Line= 4
2312944.13848012645245.0234443682313038.97779667645150.184127814
2313054.56782131645037.1564491812313153.30464402644834.486128875
#Sta/Elev= 30
       0    3183     5.6 3180.93    39.6 3163.81      51 3160.81    73.6    3149
   107.3 3136.35   139.2 3117.55   151.3 3109.11   159.4 3102.39   163.4 3100.17
   171.4 3098.34   179.6  3098.4   187.6  3095.5   195.7  3094.9   203.8  3093.8
  212.523094.911   219.9 3097.07     224 3099.34   248.2 3104.74   253.4 3106.68
   301.6 3133.77   333.2 3147.86     355 3159.42     405 3183.32   430.6 3199.31
   437.9 3203.07   448.4 3207.83   457.3 3209.15   466.2 3213.45   473.7 3215.93
#Mann= 3 ,-1,0
       0      .1       0   195.7    .045       0  212.52      .1       0
Bank Sta=195.7,212.52
XS Rating Curve= 0 ,0
Exp/Cntr(USF)=0,0
Exp/Cntr=0.3,0.1

Type RM Length L Ch R = 1 ,819     ,139,145.8,151
XS GIS Cut Line= 3
2313061.19029354645290.022649735 2313223.4597549645156.679971414
2313321.22237455644896.301155136
#Sta/Elev= 30
       0 3172.52       9 3166.27    24.6 3159.94    45.4 3147.02      66  3140.4
    83.2 3131.79    91.9 3129.56   133.4 3112.14   164.7 3103.05   190.3 3098.34
     218 3086.93   230.9  3086.7   239.4 3081.83   246.2 3081.14   252.2 3080.35
  264.073081.156   277.9 3084.17   286.4 3101.73     290 3106.38   307.8 3120.51
   316.3 3124.78   337.2 3139.41   346.2 3143.81   372.1 3160.36     406 3179.14
   423.1 3184.71     453 3199.57   465.9 3202.99   482.9 3210.68   488.2 3211.56
#Mann= 3 ,-1,0
       0      .1       0   246.2    .045       0  264.07      .1       0
Bank Sta=246.2,264.07
XS Rating Curve= 0 ,0
Exp/Cntr(USF)=0,0
Exp/Cntr=0.3,0.1