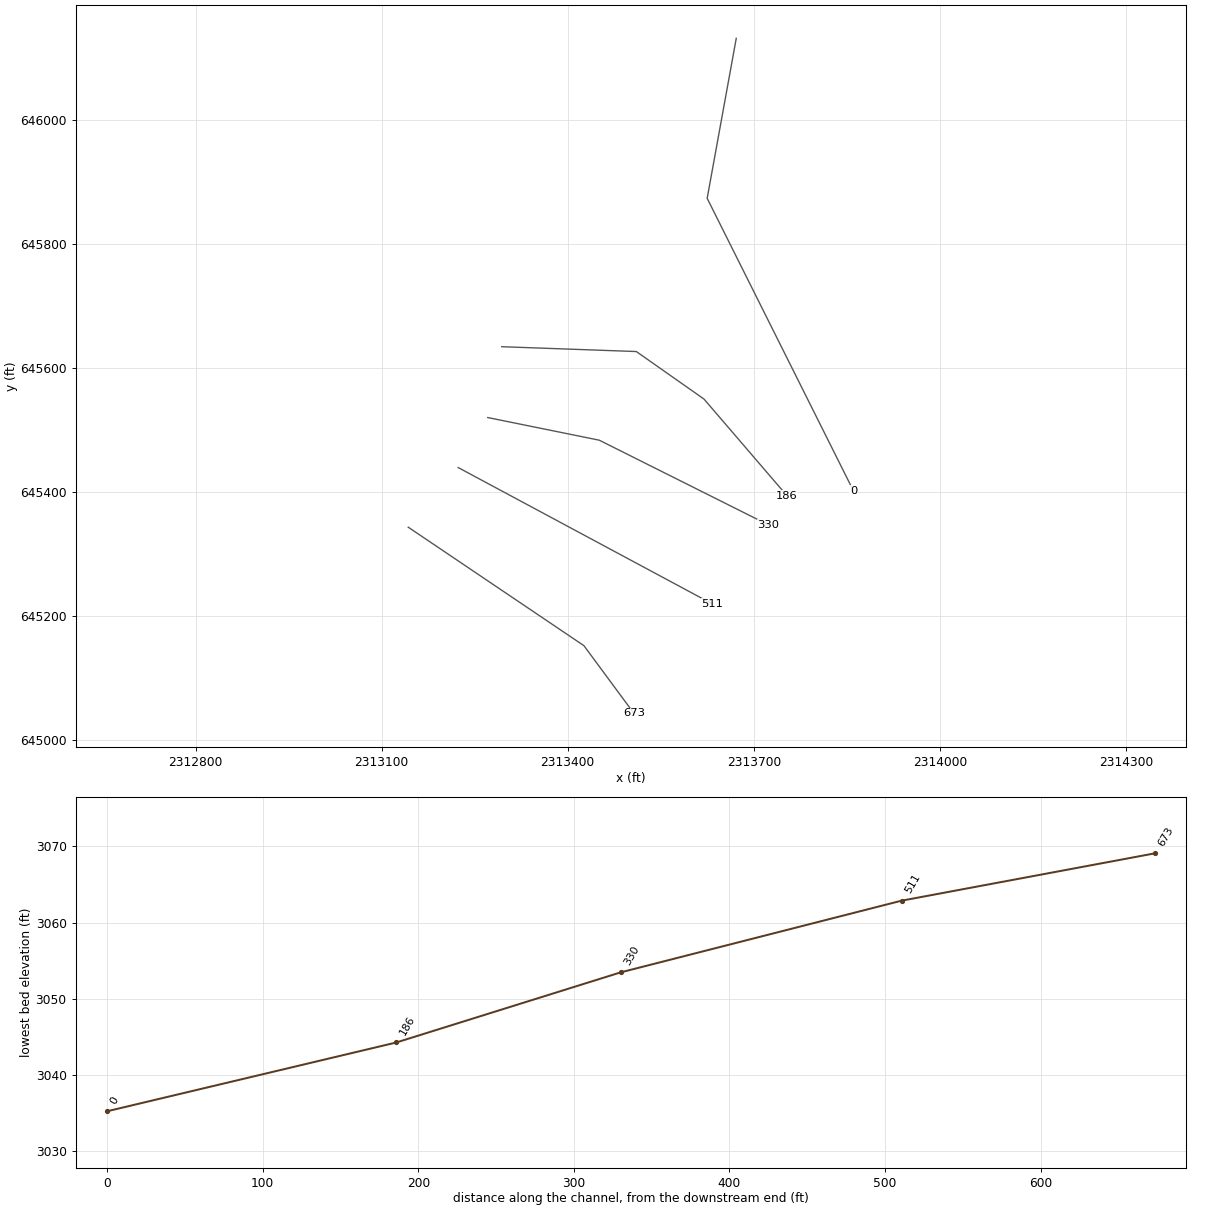
HEC-RAS study ROSERN.prj: ROSERN

--- ROSERN.g01 (geometry) --- (continued)

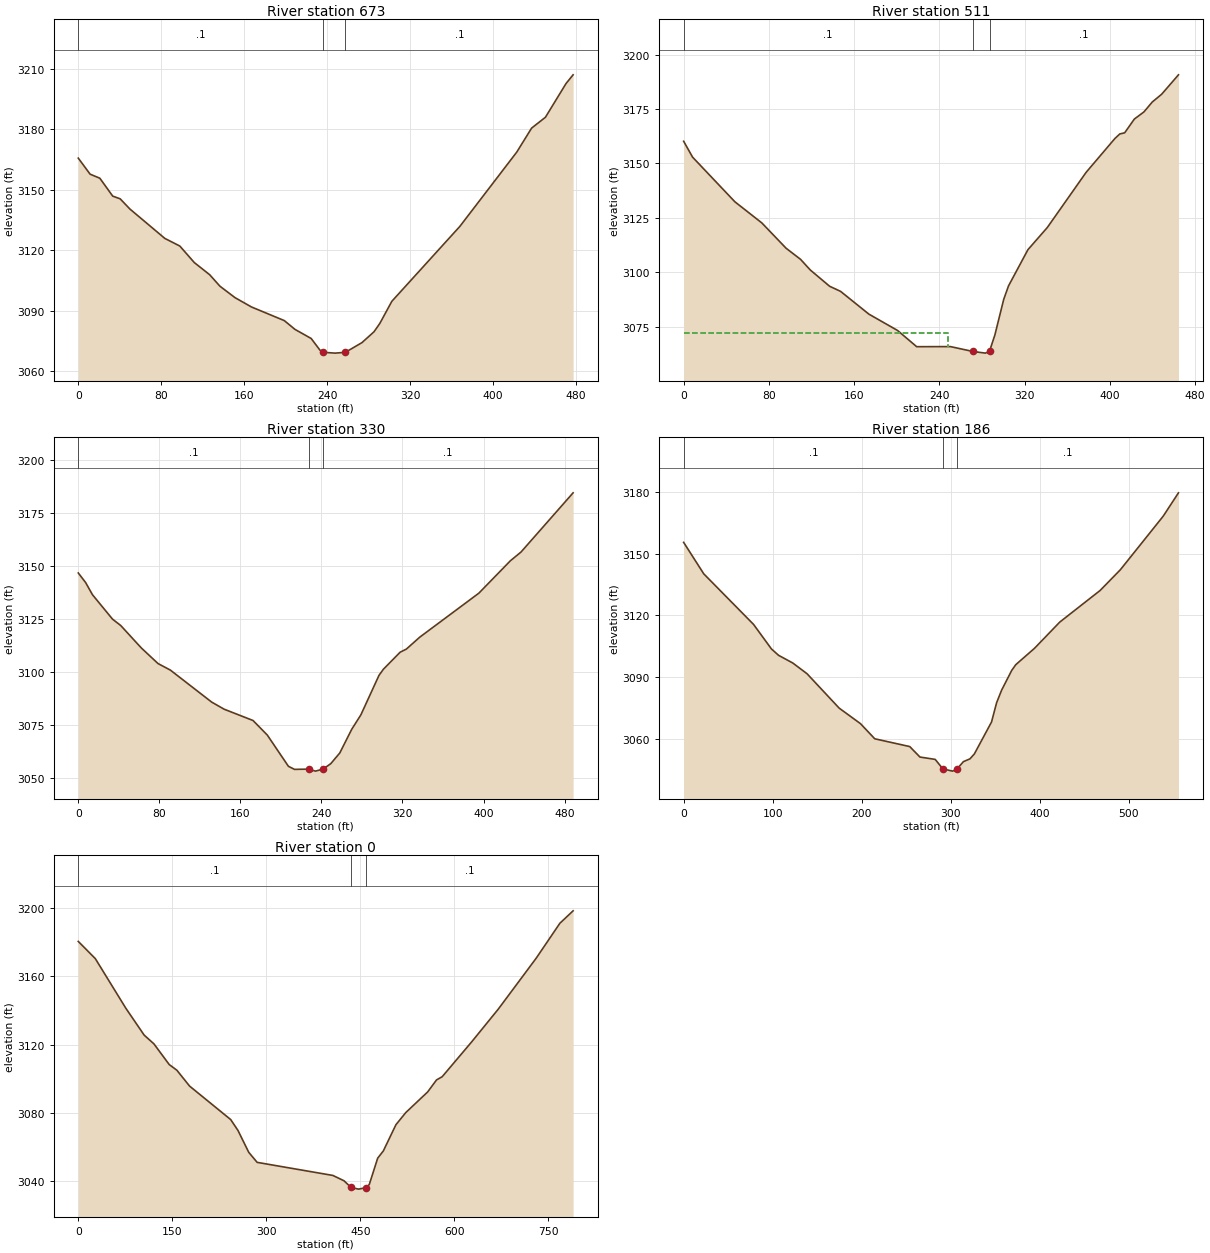
Type RM Length L Ch R = 1 ,673     ,160.8,162.6,160.6
XS GIS Cut Line= 3
2313142.91129426645343.760267081 2313426.1300752645152.782465254
2313506.67853584645043.652292781
#Sta/Elev= 30
       0 3165.75    11.4 3157.81    20.8 3155.79    33.2 3146.93    40.4 3145.58
    49.8 3140.52    83.5 3125.95    97.9 3122.19   111.9 3113.98   126.7 3107.97
   136.6 3102.27   151.1 3096.61     167 3091.98   198.7 3085.21     209 3080.85
   224.6 3076.35   233.1 3070.55   236.2  3069.5   247.7 3069.09  257.623069.499
   273.6 3074.31   285.2 3079.68   290.8 3083.81   302.4 3094.78     368 3131.92
   422.9 3168.77   437.2 3180.64   450.5 3186.01   470.4 3202.75   477.2 3207.05
#Mann= 3 ,-1,0
       0      .1       0   236.2    .045       0  257.62      .1       0
Bank Sta=236.2,257.62
XS Rating Curve= 0 ,0
Exp/Cntr(USF)=0,0
Exp/Cntr=0.3,0.1

Type RM Length L Ch R = 1 ,511     ,176.3,180.6,177.7
XS GIS Cut Line= 2
 2313223.4597549645439.8987523552313632.69790167645220.339238689
#Sta/Elev= 30
       0 3160.21     8.4 3152.91    48.1  3132.4    73.4 3122.69    96.1 3111.09
   109.8 3105.93   118.8  3101.1     137  3093.6   147.3 3091.25   173.9 3080.78
   200.8 3073.28   218.7 3065.84   250.5 3065.87   271.4 3063.65   283.2 3062.88
  287.053063.734   292.1 3071.22   300.4 3087.59   304.9 3093.76   323.1 3110.39
   341.3 3120.58   377.7 3145.91   404.8 3161.51   409.4 3163.58   413.9 3164.09
     423 3170.41     432  3173.7   439.8 3178.24   448.6  3181.8   464.4 3190.73
#Mann= 3 ,-1,0
       0      .1       0   271.4    .045       0  287.05      .1       0
#XS Ineff= 2 , 0
          247.76 3072.29
Permanent Ineff=
       F       F
Bank Sta=271.4,287.05
XS Rating Curve= 0 ,0
Exp/Cntr(USF)=0,0
Exp/Cntr=0.3,0.1

Type RM Length L Ch R = 1 ,330     ,144.9,144.2,142.9
XS GIS Cut Line= 3
2313271.07545976645520.5626152392313450.81428088645484.070488832
2313723.52334724645347.542106733
#Sta/Elev= 30
       0 3146.78     7.2 3142.32      14 3136.55    33.8 3125.04    41.9 3122.04
    62.3 3111.43    78.7 3104.13    90.9 3101.04   131.7 3085.96     144 3082.62
   172.5  3077.3   186.6 3070.43   207.4 3055.74   213.4 3054.29  227.59  3054.4
   234.1 3053.46  241.623054.414   249.2 3056.97   258.1    3062   269.9 3073.17
   278.9 3079.94   296.8 3098.56   301.2 3101.47   317.7 3109.48   323.9 3110.96
     337 3116.54   395.4 3137.28   426.5 3152.53     437 3156.65   488.4 3184.53
#Mann= 3 ,-1,0
       0      .1       0  227.59    .045       0  241.62      .1       0
Bank Sta=227.59,241.62
XS Rating Curve= 0 ,0
Exp/Cntr(USF)=0,0
Exp/Cntr=0.3,0.1

Type RM Length L Ch R = 1 ,186     ,191.2,185.8,180.4
XS GIS Cut Line= 4
2313293.61486577645634.774060342  2313510.576042645626.979048023
2313619.70621447645550.3280935482313753.52059262645394.427847158
#Sta/Elev= 30
       0 3155.57    22.6 3140.26    78.6 3115.62    98.6 3103.73   106.6 3100.62
   122.6 3096.87   138.6 3091.66   174.7 3074.92   198.7 3067.34   214.7 3059.99
     254  3056.2   265.5  3051.1   282.6 3049.96   291.3 3045.31   302.2 3044.25
     307 3045.27   314.3 3048.86   321.7 3050.24   326.6 3052.62   345.9 3068.17
   351.6 3077.54   357.2 3083.64   368.6 3093.28   373.1 3096.04   394.2 3104.03
   422.5 3116.76   467.9 3132.17   490.6 3142.24   538.8 3168.34   555.9 3179.68
#Mann= 3 ,-1,0
       0      .1       0   291.3    .045       0     307      .1       0
Bank Sta=291.3,307
XS Rating Curve= 0 ,0
Exp/Cntr(USF)=0,0
Exp/Cntr=0.3,0.1

Type RM Length L Ch R = 1 ,0       ,,,
XS GIS Cut Line= 3
2313671.68253824646131.9018663142313624.79165998645874.002035879
2313860.62519476645402.334966313
#Sta/Elev= 30
       0 3180.51    27.2 3170.41    75.9 3141.31   105.1 3125.56   120.7 3120.42
   145.1 3108.28   157.3 3104.96   177.6 3095.65   243.2 3076.01   254.8 3069.64
     272  3056.8   285.4 3050.92   406.2 3043.25     424 3040.12   435.2  3036.2
   447.1 3035.22   459.8 3036.12   464.3 3037.95   477.7 3053.38   486.7 3057.61
   506.8 3072.98   522.4 3080.07   557.4 3092.21   571.6 3099.27   580.6 3101.15
   627.5 3121.52     670 3140.74   730.4 3170.56   768.4 3191.15   789.5 3198.45
#Mann= 3 ,-1,0
       0      .1       0   435.2    .045       0   459.8      .1       0
Bank Sta=435.2,459.8
XS Rating Curve= 0 ,0
Exp/Cntr=0.3,0.1
LCMann Table=0

Chan Stop Cuts=-1
Use User Specified Reach Order=0
Composite Channel Slope=5